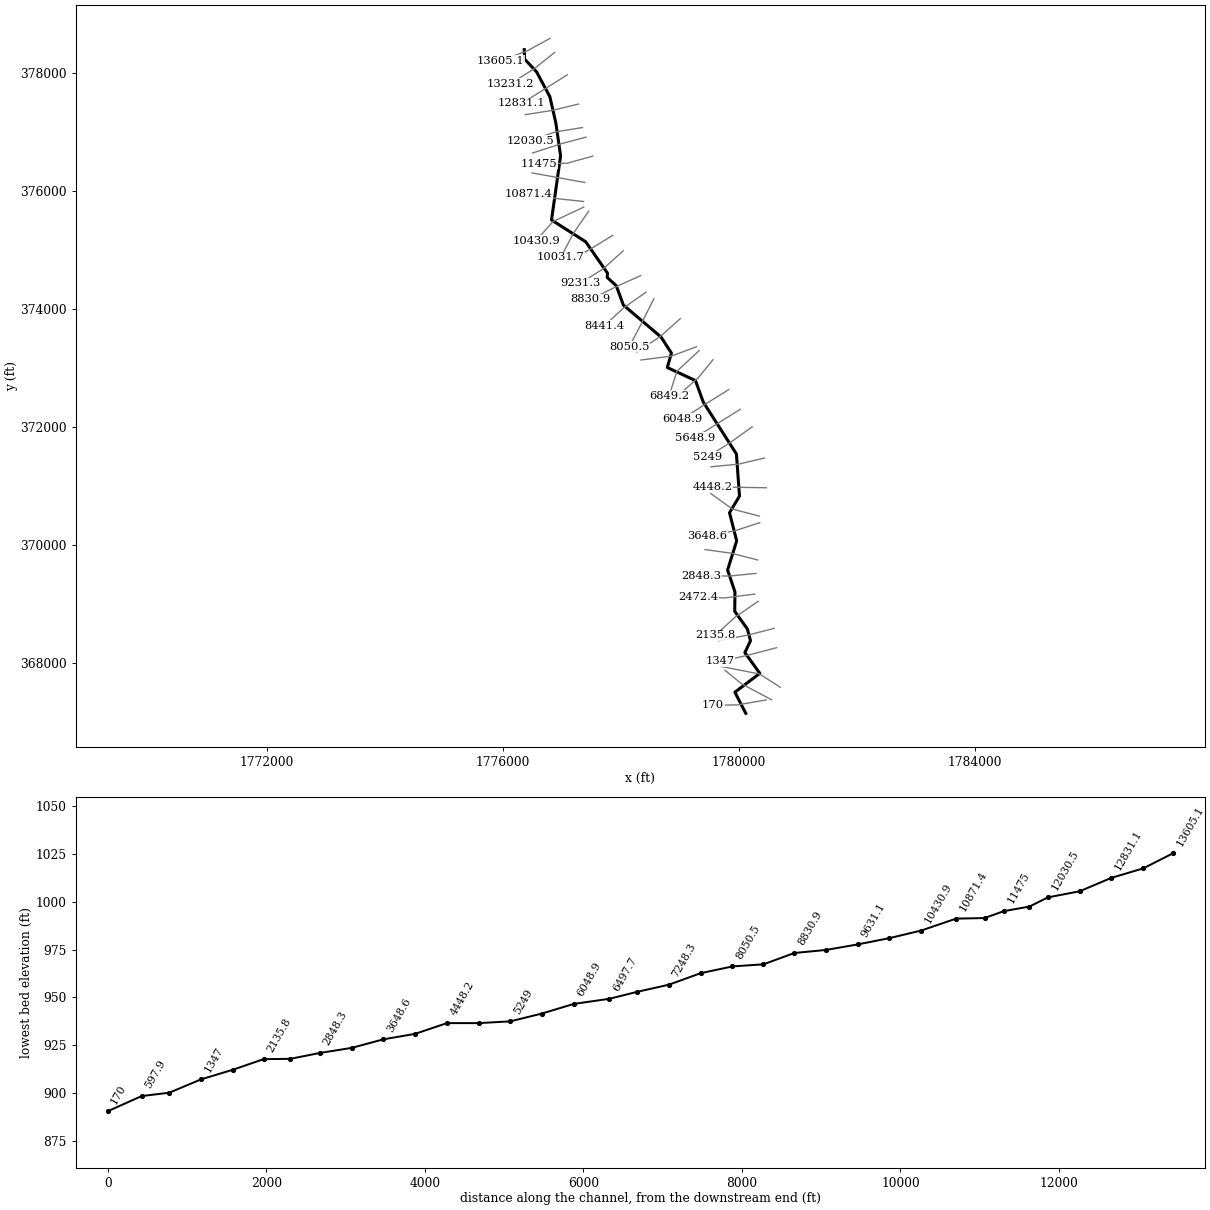
--- FnchsRn.prj (project) ---

Proj Title=FnchsRn
Current Plan=p01
Default Exp/Contr=0,0
English Units
Geom File=g01
Flow File=f01
Plan File=p01
BEGIN DESCRIPTION:
END DESCRIPTION:
DSS Export Rating Curves= 0
DSS Export Rating Curve Sorted= 0
DSS Export Volume Flow Curves= 0
DXF OffsetX= 0
DXF OffsetY= 0
DXF ScaleX= 0
DXF ScaleY= 0

--- FnchsRn.p01 (plan) ---

Plan Title=Floodplain
Program Version=4.00
Geom File=g01
Flow File=f01
K Sum by GR=0
Std Step Tol=0.01
Critical Tol=0.01
Num of Std Step Trials=20
Max Error Tol=0.3
Flow Tol Ratio=0.001
Split Flow NTrial=30
Split Flow Tol=0.02
Split Flow Ratio=0.02
Log Output Level=0
Friction Slope Method=1
Unsteady Friction Slope Method=2
Unsteady Bridges Friction Slope Method=1
Global Log Level=0
CheckData=False
Run HTab=0
Run UNet=0
Run PostProcess=0
UNET Theta=0
UNET Theta Warmup=0
UNET ZTol=0
UNET ZSATol=0
UNET MxIter=0
UNET MaxInSteps=0
UNET DtIC=0
UNET DtMin=0
UNET MaxCRTS=0
UNET WFStab=0
UNET SFStab=0
UNET WFX=0
UNET SFX=0
UNET DSS MLevel=0
UNET DZMax Abort=0
UNET Convert EG Bridges=0
UNET Use Existing IB Tables=0
UNET Froude Limit=0
UNET Froude Power=0
Write IC File=0
Echo Input=False
Echo Output=False
Write Detailed=0

--- FnchsRn.f01 (steady flow) ---

Flow Title=NFF Regression Equation
Program Version=4.00
Number of Profiles= 1
Profile Names=P100yr
River Rch & RM=FnchsRn,Main            ,13605.1
 851.448
River Rch & RM=FnchsRn,Main            ,11797.7
892.9082
River Rch & RM=FnchsRn,Main            ,11230.2
986.0567
River Rch & RM=FnchsRn,Main            ,10430.9
992.9717
River Rch & RM=FnchsRn,Main            ,10430.9
1178.014
River Rch & RM=FnchsRn,Main            ,6497.7
1299.601
River Rch & RM=FnchsRn,Main            ,6048.9
1595.617
River Rch & RM=FnchsRn,Main            ,4848.5
1615.486
River Rch & RM=FnchsRn,Main            ,170
1789.681
Boundary for River Rch & Prof#=FnchsRn,Main            , 1
Up Type= 0
Dn Type= 3
Dn Slope=0.00843
DSS Import GetInterval= 0
DSS Import GetPeak= 0
DSS Import FillOption= 0

--- FnchsRn.g01 (geometry) ---

Geom Title=USGS 3m DEM
Program Version=4.00

River Reach=FnchsRn     ,Main
Reach XY= 30
     1776361.529      378396.575     1776365.870      378238.155
     1776569.863      378021.141     1776795.557      377600.134
     1776897.554      377153.086     1776977.849      376597.530
     1776823.769      375510.291     1777403.196      375141.367
     1777774.290      374607.513     1777767.779      374535.898
     1777921.859      374397.009     1778042.120      374069.187
     1778681.408      373526.783     1778857.189      373255.516
     1778787.745      373010.290     1779265.175      372788.936
     1779397.554      372424.353     1779959.620      371545.447
     1780011.703      370831.471     1779842.432      370549.353
     1779963.960      370074.093     1779809.880      369579.301
     1779934.933      369207.083     1779930.777      368878.753
     1780144.815      368581.593     1780198.335      368381.384
     1780102.849      368179.561     1780356.755      367827.999
     1779933.578      367508.988     1780118.715      367149.958

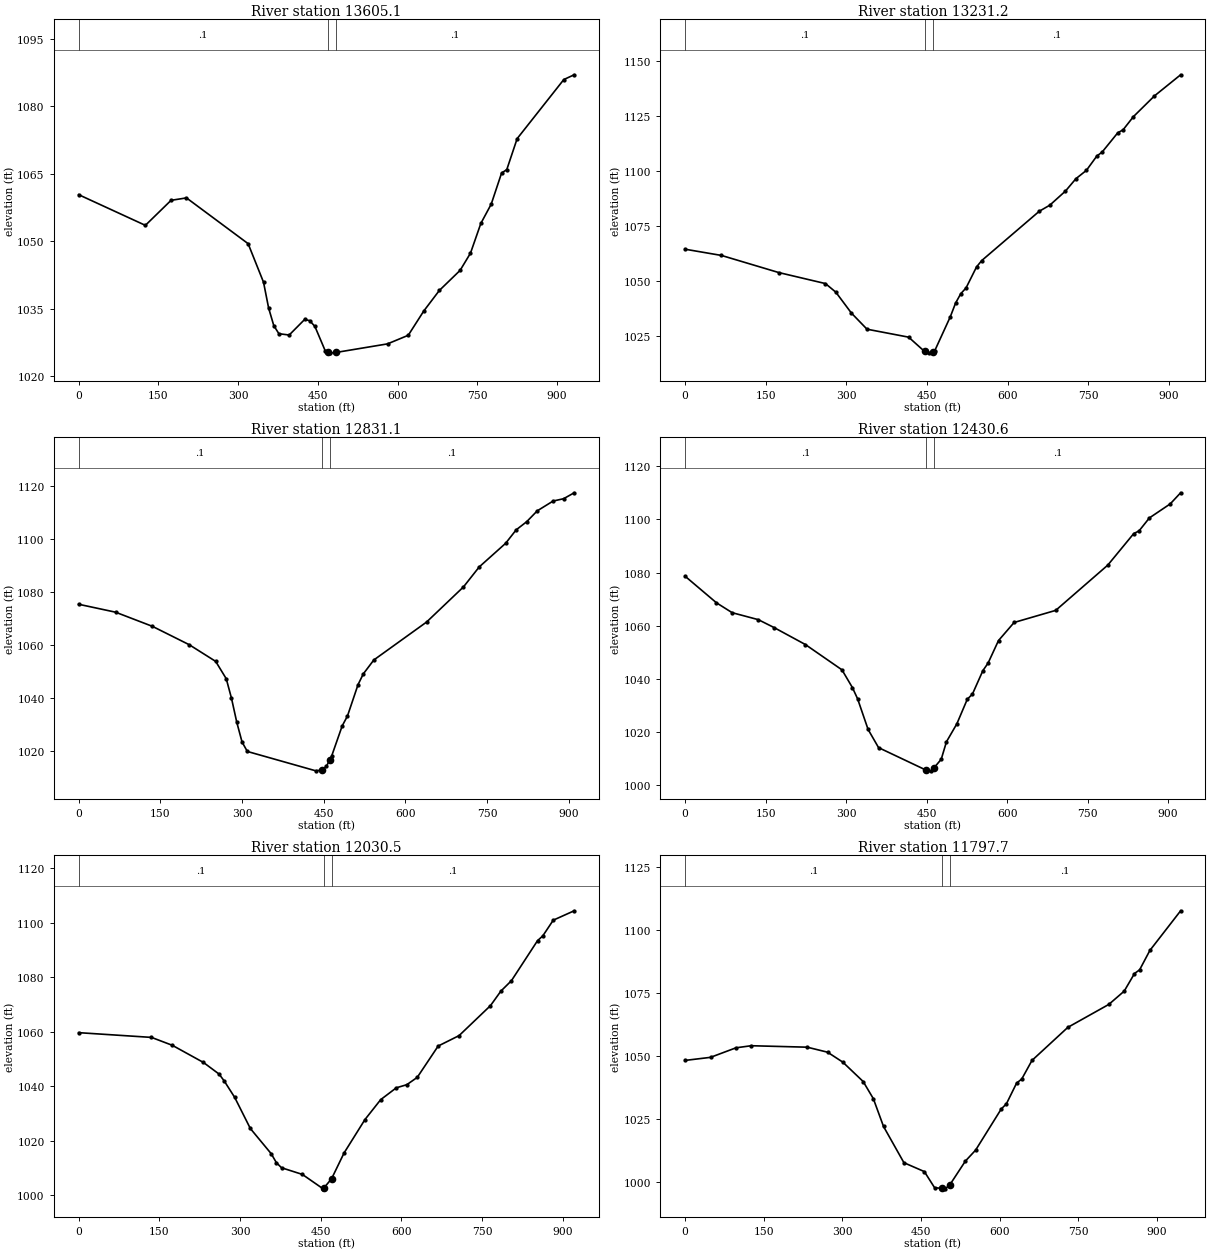
Type RM Length L Ch R = 1 ,13605.1,366.571,373.91,377.457
XS GIS Cut Line= 3
     1776800.263      378588.182     1776418.532      378379.965
     1775953.515      378202.981
#Sta/Elev= 30
       0 1060.36   125.6 1053.54   173.9 1059.10   202.9 1059.64   318.9 1049.47
   347.9 1040.90   357.5 1035.16   367.2 1031.26   376.8 1029.46   396.2 1029.17
   425.2 1032.62   434.8 1032.36   444.6 1031.07   464.1 1025.63     469 1025.42
   473.8 1025.21     484 1025.29   581.2 1027.20   620.2 1029.11   649.5 1034.52
   678.7 1039.07   717.8 1043.54   737.3 1047.36   756.8 1053.97   776.3 1058.25
   795.8 1065.16   805.6 1065.93   825.1 1072.81   912.9 1085.94   932.4 1087.00
#Mann= 3 , 0 , 0
       0     0.1       0     469   0.045       0     484     0.1       0
Bank Sta=     469,     484
Exp/Cntr=0.3,0.1

Type RM Length L Ch R = 1 ,13231.2,403.404,400.161,399.236
XS GIS Cut Line= 3
     1776879.564      378351.231     1776524.039      378068.204
     1776127.579      377820.741
#Sta/Elev= 30
       0 1064.41    67.7 1061.58   174.0 1053.83   261.1 1048.81   280.4 1044.91
   309.4 1035.41   338.4 1028.10   415.8 1024.49   445.5 1017.99   454.4 1017.37
   460.5 1017.90   464.2 1018.22   493.4 1033.78   503.1 1039.93   512.8 1044.22
   522.6 1046.82   542.1 1056.35   551.8 1059.26   658.9 1081.65   678.4 1084.39
   707.6 1090.81   727.0 1096.42   746.5 1100.20   766.0 1106.73   775.7 1108.48
   804.9 1117.27   814.7 1118.60   834.1 1124.62   873.1 1134.00   921.8 1143.59
#Mann= 3 , 0 , 0
       0     0.1       0   445.5   0.045       0   460.5     0.1       0
Bank Sta=   445.5,   460.5
Exp/Cntr=0.3,0.1

Type RM Length L Ch R = 1 ,12831.1,407.374,400.448,391.754
XS GIS Cut Line= 3
     1777091.649      377969.788     1776706.314      377727.834
     1776320.979      377485.879
#Sta/Elev= 30
       0 1075.27    67.8 1072.28   135.5 1066.94   203.3 1059.99   251.7 1053.72
   271.1 1047.17   280.7 1039.83   290.4 1030.78   300.1 1023.32   309.8 1019.76
   435.6 1012.45   446.1 1012.74   455.0 1014.13   461.1 1016.60   464.7 1018.06
   484.0 1029.40   493.7 1033.14   513.1 1044.96   522.8 1049.02   542.1 1054.26
   638.9 1068.55   706.7 1081.81   735.7 1089.36   784.1 1098.25   803.5 1103.33
   822.9 1106.42   842.2 1110.50   871.3 1114.19   890.6 1115.07   910.0 1117.31
#Mann= 3 , 0 , 0
       0     0.1       0   446.1   0.045       0   461.1     0.1       0
Bank Sta=   446.1,   461.1
Exp/Cntr=0.3,0.1

Type RM Length L Ch R = 1 ,12430.6,399.351,400.145,403.306
XS GIS Cut Line= 3
     1777284.209      377475.086     1776839.092      377367.553
     1776379.342      377294.933
#Sta/Elev= 30
       0 1078.62    58.5 1068.62    87.7 1064.91   136.4 1062.29   165.6 1059.34
   224.1 1052.94   292.3 1043.42   311.8 1036.74   321.5 1032.50   341.0 1021.00
   360.5 1014.17     449 1005.71   457.9 1005.44     464 1006.61   477.3 1009.80
   487.0 1016.36   506.4 1023.12   525.8 1032.34   535.5 1034.33   554.9 1043.12
   564.6 1045.96   584.0 1054.43   613.1 1061.23   690.6 1065.78   787.6 1082.79
   836.1 1094.68   845.8 1095.64   865.2 1100.55   904.0 1105.82   923.4 1110.00
#Mann= 3 , 0 , 0
       0     0.1       0     449   0.045       0     464     0.1       0
Bank Sta=     449,     464
Exp/Cntr=0.3,0.1

Type RM Length L Ch R = 1 ,12030.5,229.435,232.809,232.39
XS GIS Cut Line= 3
     1777350.129      377076.806     1776891.697      377002.505
     1776458.686      376856.146
#Sta/Elev= 30
       0 1059.59   135.5 1057.85   174.2 1054.95   232.2 1048.64   261.2 1044.38
   270.9 1041.81   290.3 1035.80   319.3 1024.41   358.0 1015.18   367.7 1011.88
   377.3 1010.00   416.0 1007.56   454.7 1002.26   455.4 1002.42   470.4 1005.97
   493.6 1015.43   532.5 1027.71   561.7 1035.00   590.8 1039.35   610.3 1040.49
   629.7 1043.18   668.6 1054.68   707.5 1058.51   765.9 1069.52   785.3 1074.86
   804.8 1078.66   853.4 1093.37   863.1 1095.10   882.6 1100.88   921.5 1104.33
#Mann= 3 , 0 , 0
       0     0.1       0   455.4   0.045       0   470.4     0.1       0
Bank Sta=   455.4,   470.4
Exp/Cntr=0.3,0.1

Type RM Length L Ch R = 1 ,11797.7,329.807,322.662,315.517
XS GIS Cut Line= 3
     1777407.398      376913.523     1776994.599      376804.457
     1776501.819      376644.824
#Sta/Elev= 30
       0 1048.43    48.5 1049.65    97.0 1053.43   126.1 1054.26   232.9 1053.68
   271.7 1051.69   300.8 1047.74   339.6 1040.05   359.0 1033.24   378.4 1022.22
   417.3 1007.84   456.3 1004.31   475.8  997.91   489.5  997.68   495.4  997.47
   504.5  998.95   534.5 1008.48   554.0 1012.83   602.9 1029.16   612.7 1031.19
   632.2 1039.43   642.0 1041.05   661.5 1048.42   729.9 1061.55   808.1 1070.66
   837.4 1075.93   857.0 1082.91   866.8 1084.39   886.3 1092.06   945.0 1107.81
#Mann= 3 , 0 , 0
       0     0.1       0   489.5   0.045       0   504.5     0.1       0
Bank Sta=   489.5,   504.5
Exp/Cntr=0.3,0.1

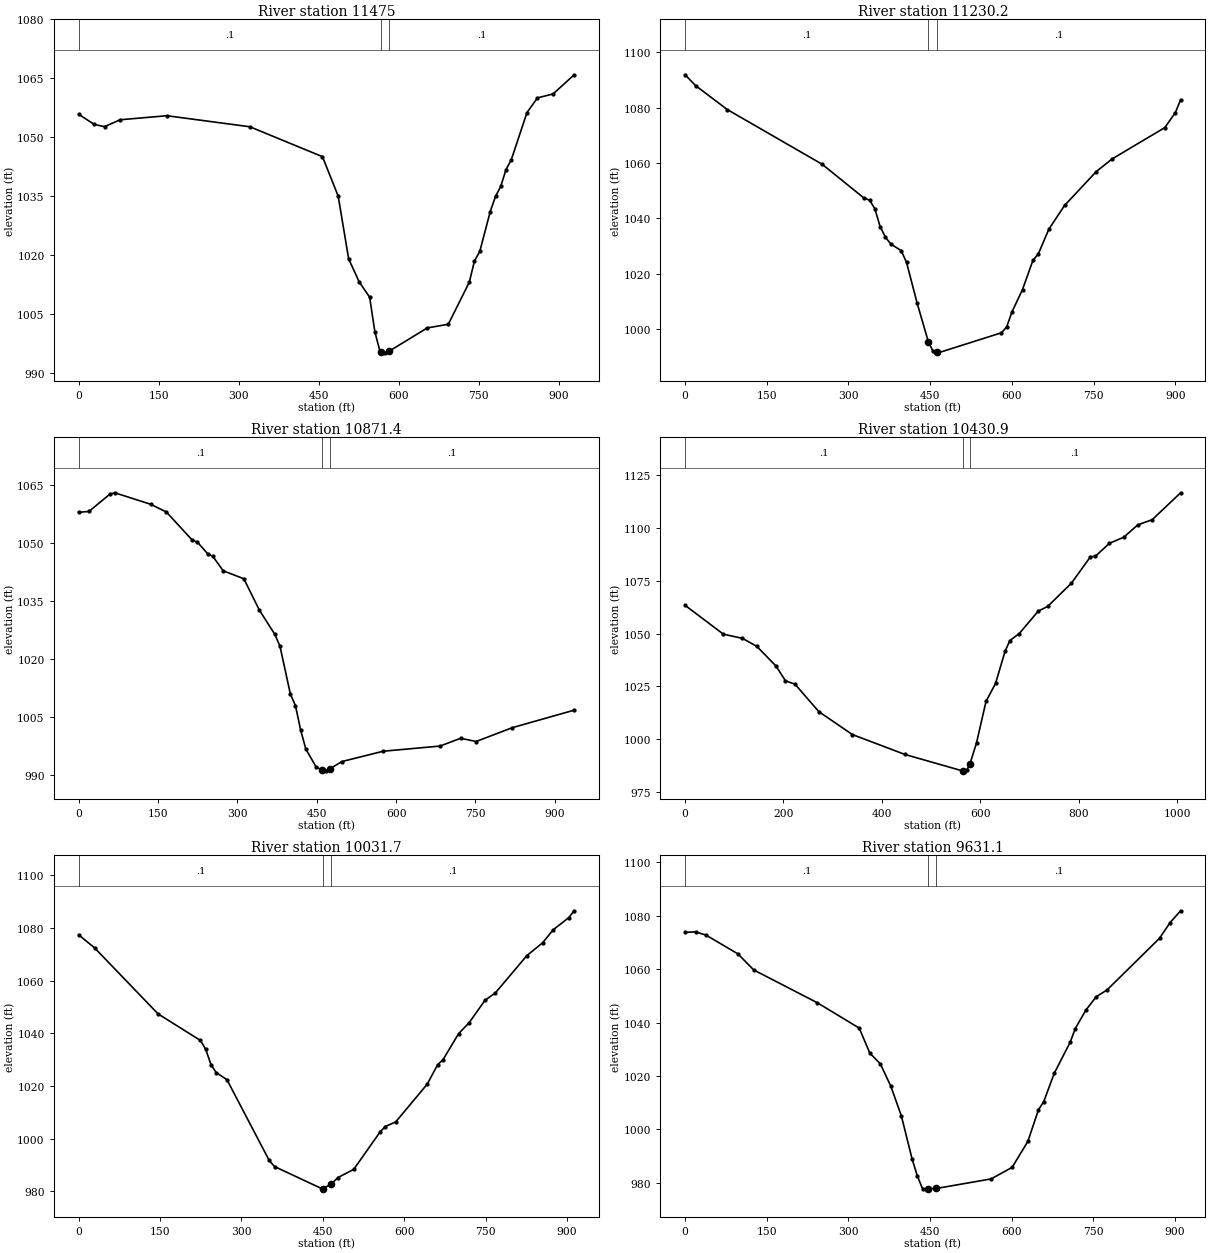
Type RM Length L Ch R = 1 ,11475,249.202,244.817,240.431
XS GIS Cut Line= 3
     1777525.553      376592.770     1777084.827      376471.310
     1776612.868      376464.369
#Sta/Elev= 30
       0 1055.86    29.2 1053.27    48.6 1052.69    77.8 1054.45   165.4 1055.48
   321.0 1052.67   457.2 1045.05   486.7 1035.00   506.3 1019.03   526.0 1013.17
   545.7 1009.25   555.5 1000.41   565.3  995.32   567.8  995.26   575.2  995.08
   582.8  995.54   653.8 1001.43   693.2 1002.36   732.5 1013.06   742.3 1018.51
   752.2 1020.90   771.8 1031.06   781.7 1034.92   791.5 1037.47   801.3 1041.74
   811.2 1044.23   840.7 1056.28   860.3 1060.02   889.8 1061.04   929.2 1065.91
#Mann= 3 , 0 , 0
       0     0.1       0   567.8   0.045       0   582.8     0.1       0
Bank Sta=   567.8,   582.8
Exp/Cntr=0.3,0.1

Type RM Length L Ch R = 1 ,11230.2,357.585,358.797,359.379
XS GIS Cut Line= 3
     1777390.292      376144.825     1776942.631      376226.217
     1776494.970      376307.610
#Sta/Elev= 30
       0 1091.89    19.4 1087.96    77.4 1079.34   251.7 1059.57   329.1 1047.27
   338.8 1046.62   348.5 1043.47   358.2 1037.04   367.9 1033.23   377.6 1030.80
   396.9 1028.36   406.6 1024.15   426.0 1009.49   446.7  995.45   455.0  992.15
   461.7  991.67   464.7  991.46   580.9  998.70   590.5 1000.80   600.2 1006.22
   619.6 1014.31   638.9 1024.95   648.6 1027.16   668.0 1036.12   697.0 1044.72
   755.1 1056.93   784.1 1061.49   881.0 1072.82   900.3 1078.22   910.0 1082.90
#Mann= 3 , 0 , 0
       0     0.1       0   446.7   0.045       0   461.7     0.1       0
Bank Sta=   446.7,   461.7
Exp/Cntr=0.3,0.1

Type RM Length L Ch R = 1 ,10871.4,427.97,440.537,462.058
XS GIS Cut Line= 3
     1777366.948      375823.809     1776910.952      375872.588
     1776438.528      375944.653
#Sta/Elev= 30
       0 1057.95    19.5 1058.19    58.5 1062.59    68.3 1063.01   136.6 1060.02
   165.9 1058.03   214.7 1050.78   224.4 1050.28   243.9 1047.25   253.7 1046.57
   273.2 1042.85   312.2 1040.80   341.5 1032.70   370.8 1026.42   380.5 1023.36
   400.1 1011.04   409.8 1007.99   419.6 1001.70   429.3  996.81   448.8  992.16
   460.3  991.34   468.4  991.16   475.3  991.73   497.6  993.56   575.6  996.23
   682.9  997.56   721.9  999.57   751.2  998.74   819.5 1002.31   936.5 1006.84
#Mann= 3 , 0 , 0
       0     0.1       0   460.3   0.045       0   475.3     0.1       0
Bank Sta=   460.3,   475.3
Exp/Cntr=0.3,0.1

Type RM Length L Ch R = 1 ,10430.9,386.8,399.19,405.247
XS GIS Cut Line= 3
     1777369.240      375728.196     1776850.300      375484.662
     1776561.334      375160.671
#Sta/Elev= 30
       0 1063.41    77.7 1049.74   116.6 1047.74   145.7 1043.97   184.6 1034.67
   204.0 1027.65   223.5 1026.00   272.0 1012.97   340.1 1002.13   446.9  992.70
   563.5  984.93   564.1  984.96   573.2  985.49   579.1  988.23   592.5  998.27
   611.8 1017.89   631.1 1026.37   650.4 1041.54   660.1 1046.69   679.4 1050.04
   718.0 1060.67   737.2 1062.91   785.5 1073.94   824.1 1086.45   833.7 1086.59
   862.7 1092.83   891.6 1095.67   920.5 1101.59   949.5 1103.99  1007.4 1116.77
#Mann= 3 , 0 , 0
       0     0.1       0   564.1   0.045       0   579.1     0.1       0
Bank Sta=   564.1,   579.1
Exp/Cntr=0.3,0.1

Type RM Length L Ch R = 1 ,10031.7,410.18,400.613,387.417
XS GIS Cut Line= 3
     1777453.444      375658.875     1777192.770      375281.437
     1776982.875      374878.235
#Sta/Elev= 30
       0 1077.35    29.3 1072.41   146.4 1047.35   224.5 1037.28   234.2 1033.92
   244.0 1028.05   253.8 1025.04   273.3 1022.40   351.3  991.74   361.1  989.44
   448.9  980.99   449.8  981.05   464.8  982.70   478.0  985.28   507.1  988.39
   555.4 1002.52   565.1 1004.63   584.4 1006.37   642.5 1020.71   661.8 1028.11
   671.5 1029.96   700.5 1039.90   719.8 1044.04   748.9 1052.49   768.2 1055.34
   826.2 1069.48   855.2 1074.32   874.6 1079.25   903.6 1083.90   913.3 1086.46
#Mann= 3 , 0 , 0
       0     0.1       0   449.8   0.045       0   464.8     0.1       0
Bank Sta=   449.8,   464.8
Exp/Cntr=0.3,0.1

Type RM Length L Ch R = 1 ,9631.1,395.611,399.734,401.298
XS GIS Cut Line= 3
     1777860.822      375248.535     1777471.896      375010.812
     1777073.238      374791.764
#Sta/Elev= 30
       0 1073.79    19.4 1073.95    38.8 1072.71    97.0 1065.72   126.1 1059.70
   242.5 1047.46   320.0 1037.92   339.4 1028.56   358.8 1024.52   378.2 1016.09
   397.6 1004.91   417.0  989.02   426.7  982.60   436.4  977.70   446.9  977.80
   461.9  977.85   562.3  981.41   601.0  985.74   630.0  995.51   649.4 1007.32
   659.1 1010.36   678.4 1020.99   707.5 1032.53   717.1 1037.75   736.5 1044.64
   755.8 1049.71   775.2 1052.16   872.0 1071.58   891.3 1077.44   910.7 1081.86
#Mann= 3 , 0 , 0
       0     0.1       0   446.9   0.045       0   461.9     0.1       0
Bank Sta=   446.9,   461.9
Exp/Cntr=0.3,0.1

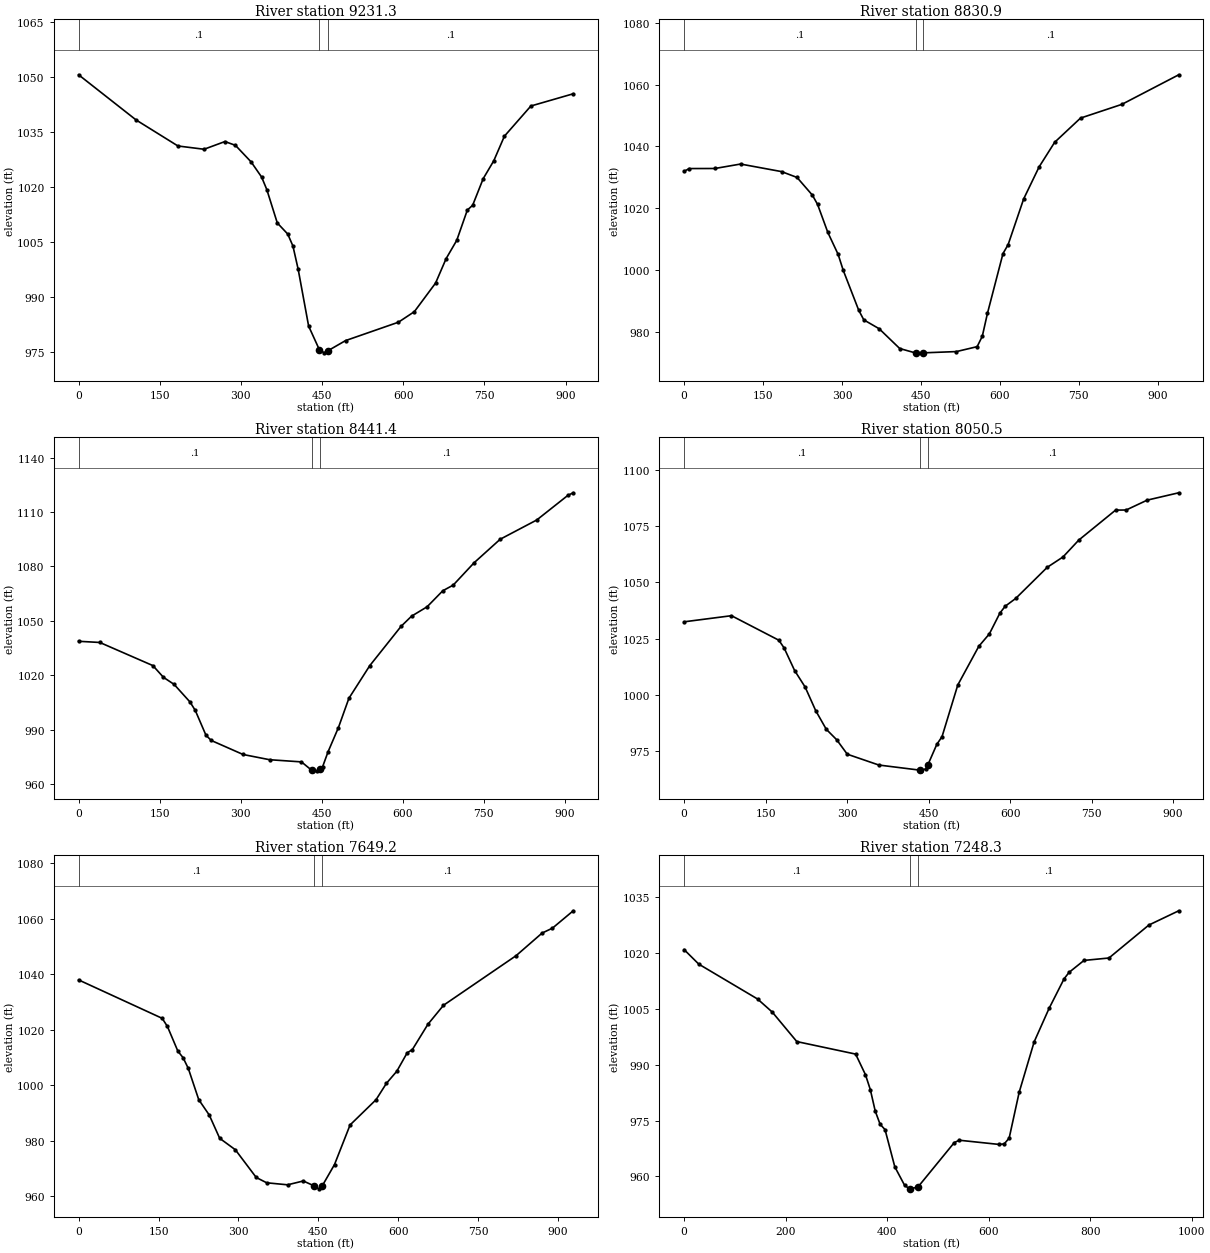
Type RM Length L Ch R = 1 ,9231.3,407.143,400.442,397.95
XS GIS Cut Line= 3
     1778040.647      374988.027     1777702.687      374684.708
     1777314.154      374438.400
#Sta/Elev= 30
       0 1050.50   106.3 1038.20   183.6 1031.12   231.9 1030.23   270.5 1032.33
   289.9 1031.29   318.8 1026.79   338.2 1022.67   347.8 1019.26   367.2 1010.17
   386.5 1007.15   396.1 1003.89   405.8  997.55   425.1  982.10   445.1  975.62
   454.1  974.82   460.1  975.33   493.3  978.15   591.1  983.16   620.5  986.03
   659.7  993.81   679.2 1000.47   698.8 1005.43   718.4 1013.69   728.2 1014.98
   747.7 1022.23   767.3 1027.11   786.9 1033.79   835.8 1042.00   914.1 1045.33
#Mann= 3 , 0 , 0
       0     0.1       0   445.1   0.045       0   460.1     0.1       0
Bank Sta=   445.1,   460.1
Exp/Cntr=0.3,0.1

Type RM Length L Ch R = 1 ,8830.9,385.267,389.454,392.879
XS GIS Cut Line= 3
     1778335.647      374567.405     1777926.522      374383.300
     1777486.276      374165.807
#Sta/Elev= 30
       0 1031.96     9.8 1032.85    58.5 1032.87   107.3 1034.31   185.3 1031.86
   214.6 1029.97   243.8 1024.23   253.6 1021.24   273.1 1012.17   292.6 1005.09
   302.3  999.93   331.6  987.06   341.4  983.88   370.6  981.01   409.6  974.61
   438.9  973.21   439.8  973.21   454.8  973.21   517.4  973.62   556.7  975.21
   566.5  978.57   576.3  986.00   605.8 1005.33   615.6 1008.24   645.1 1023.03
   674.5 1033.41   704.0 1041.36   753.1 1049.18   831.7 1053.63   939.7 1063.20
#Mann= 3 , 0 , 0
       0     0.1       0   439.8   0.045       0   454.8     0.1       0
Bank Sta=   439.8,   454.8
Exp/Cntr=0.3,0.1

Type RM Length L Ch R = 1 ,8441.4,379.791,390.893,401.913
XS GIS Cut Line= 3
     1778427.926      374287.961     1778049.908      374023.138
     1777716.171      373715.576
#Sta/Elev= 30
       0 1038.71    39.3 1038.06   137.5 1025.31   157.1 1018.84   176.8 1014.95
   206.2 1005.25   216.0 1000.58   235.7  986.94   245.5  984.05   304.4  976.32
   353.5  973.44   412.4  972.24   431.2  967.68   441.9  967.31   446.2  968.34
   451.7  969.66   461.6  977.76   480.9  991.19   500.2 1007.27   538.8 1025.26
   596.7 1046.92   616.1 1052.53   645.0 1057.74   674.0 1066.56   693.3 1069.68
   731.9 1081.99   780.2 1094.95   847.8 1105.55   905.7 1119.19   915.4 1120.56
#Mann= 3 , 0 , 0
       0     0.1       0   431.2   0.045       0   446.2     0.1       0
Bank Sta=   431.2,   446.2
Exp/Cntr=0.3,0.1

Type RM Length L Ch R = 1 ,8050.5,409.886,401.367,389.841
XS GIS Cut Line= 3
     1778559.141      374174.326     1778353.939      373767.876
     1778144.731      373363.887
#Sta/Elev= 30
       0 1032.43    87.2 1035.15   174.4 1024.25   184.1 1020.81   203.4 1010.79
   222.8 1003.43   242.2  992.96   261.6  984.70   280.9  980.01   300.3  973.60
   358.4  968.79   433.4  966.53   435.9  966.21   445.6  967.20   448.4  968.74
   465.0  977.93   474.7  981.41   503.7 1004.37   542.4 1021.56   561.8 1027.07
   581.1 1036.27   590.8 1039.33   610.2 1042.80   668.3 1056.65   697.3 1061.25
   726.3 1068.74   794.1 1082.07   813.5 1082.11   852.2 1086.50   910.3 1089.77
#Mann= 3 , 0 , 0
       0     0.1       0   433.4   0.045       0   448.4     0.1       0
Bank Sta=   433.4,   448.4
Exp/Cntr=0.3,0.1

Type RM Length L Ch R = 1 ,7649.2,406.418,400.879,392.44
XS GIS Cut Line= 3
     1779006.472      373837.772     1778670.306      373536.992
     1778272.209      373273.880
#Sta/Elev= 30
       0 1037.92   156.9 1024.08   166.7 1021.15   186.3 1012.27   196.1 1009.90
   205.9 1006.04   225.5  994.79   245.2  989.26   264.8  980.88   294.2  976.75
   333.4  966.77   353.0  964.86   392.2  964.13   421.7  965.51   442.1  963.74
   451.1  962.68   457.1  963.70   480.3  971.44   509.5  985.69   558.2  994.77
   577.7 1000.67   597.2 1005.03   616.6 1011.64   626.4 1012.83   655.6 1021.95
   684.8 1028.78   821.1 1046.65   869.8 1054.78   889.3 1056.56   928.3 1062.81
#Mann= 3 , 0 , 0
       0     0.1       0   442.1   0.045       0   457.1     0.1       0
Bank Sta=   442.1,   457.1
Exp/Cntr=0.3,0.1

Type RM Length L Ch R = 1 ,7248.3,391.81,399.111,423.016
XS GIS Cut Line= 3
     1779284.261      373363.094     1778858.969      373204.699
     1778342.530      373137.520
#Sta/Elev= 30
       0 1020.90    29.0 1016.99   144.8 1007.63   173.8 1004.11   222.1  996.20
   338.0  992.84   357.3  987.32   366.9  983.32   376.6  977.54   386.2  974.00
   395.9  972.57   415.2  962.56   434.5  957.60   444.2  956.66   445.7  956.67
   460.7  957.14   532.4  969.09   542.3  969.71   620.9  968.58   630.7  968.72
   640.5  970.29   660.2  982.59   689.7  996.12   719.1 1005.10   748.6 1013.03
   758.4 1014.77   787.9 1017.99   837.1 1018.64   915.7 1027.49   974.6 1031.32
#Mann= 3 , 0 , 0
       0     0.1       0   445.7   0.045       0   460.7     0.1       0
Bank Sta=   445.7,   460.7
Exp/Cntr=0.3,0.1

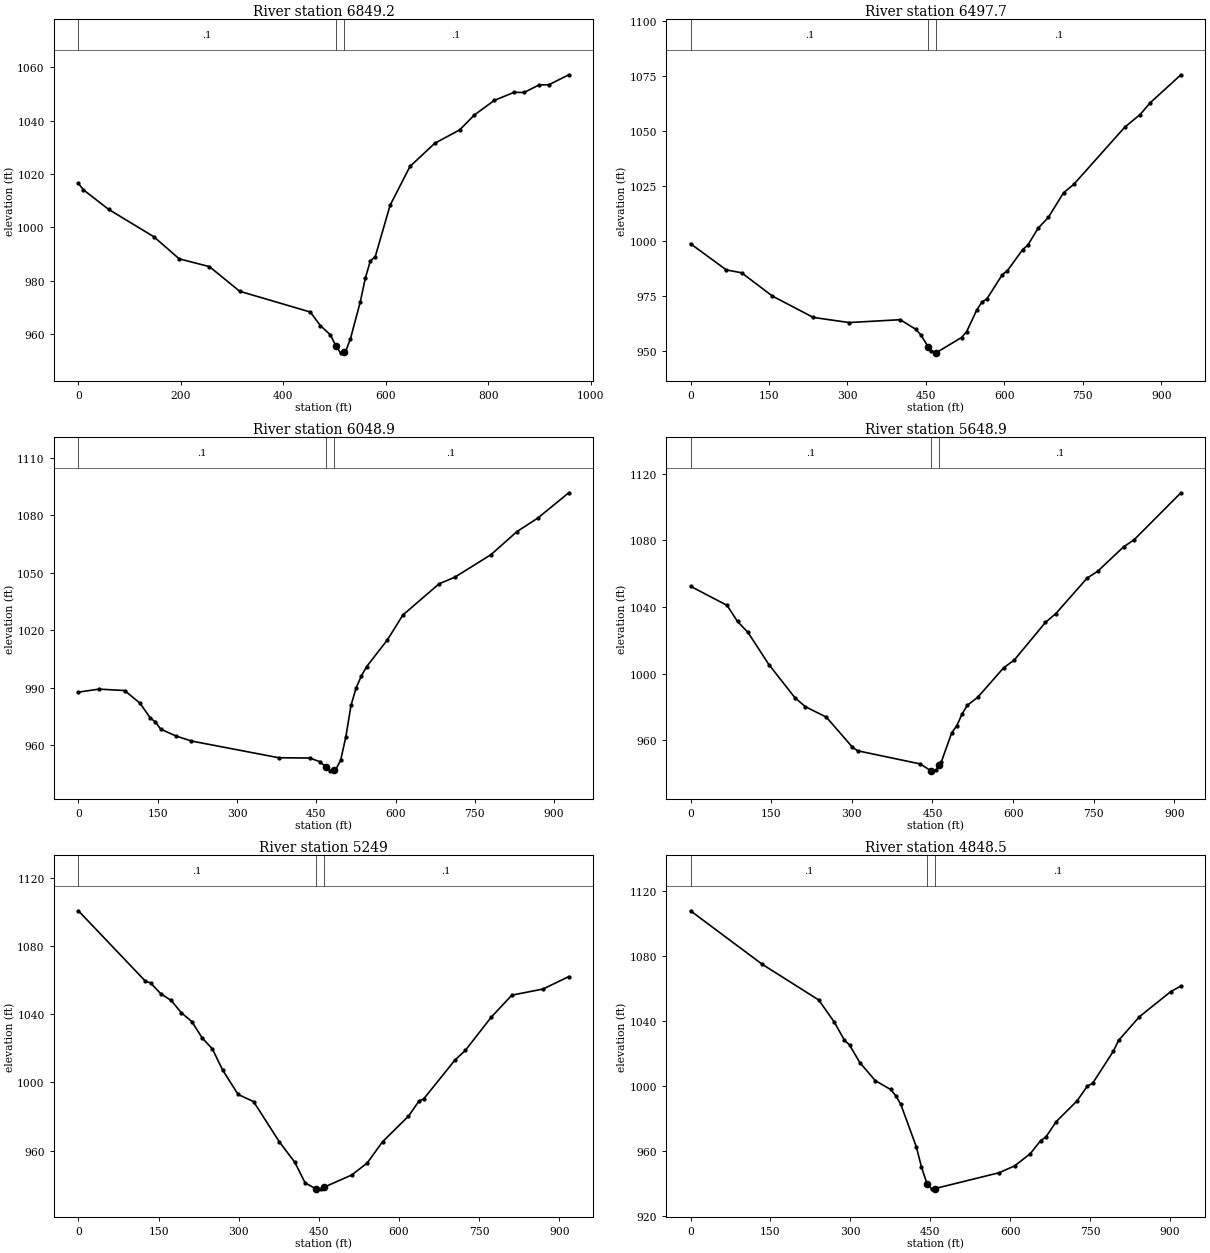
Type RM Length L Ch R = 1 ,6849.2,350.585,351.501,340.127
XS GIS Cut Line= 3
     1779329.097      373297.132     1778952.727      372950.758
     1778816.098      372526.840
#Sta/Elev= 30
       0 1016.46     9.8 1014.06    59.0 1006.72   147.5  996.43   196.7  988.18
   255.7  985.26   314.8  976.02   452.5  968.25   472.2  963.16   491.8  959.68
   502.5  955.54   511.5  952.95   517.5  953.16   521.2  953.29   530.9  958.23
   550.2  972.14   559.9  980.92   569.6  987.34   579.3  989.00   608.3 1008.28
   647.1 1022.81   695.5 1031.50   743.9 1036.49   772.9 1042.12   811.7 1047.57
   850.4 1050.60   869.7 1050.52   898.8 1053.35   918.2 1053.43   956.9 1057.16
#Mann= 3 , 0 , 0
       0     0.1       0   502.5   0.045       0   517.5     0.1       0
Bank Sta=   502.5,   517.5
Exp/Cntr=0.3,0.1

Type RM Length L Ch R = 1 ,6497.7,452.278,448.761,445.641
XS GIS Cut Line= 3
     1779561.331      373142.137     1779321.116      372845.871
     1778904.742      372477.541
#Sta/Elev= 30
       0  998.93    68.5  987.02    97.8  985.70   156.5  975.13   234.7  965.41
   303.2  963.08   400.9  964.38   430.2  960.06   439.9  957.61   454.5  951.91
   459.4  950.27   469.2  949.31   469.5  949.34   518.0  956.28   527.7  958.89
   547.2  968.83   557.0  972.35   566.7  973.92   596.0  984.88   605.7  986.67
   635.0  996.29   644.7  998.26   664.2 1005.92   683.8 1010.86   713.0 1022.07
   732.5 1025.91   830.0 1051.92   859.3 1057.65   878.8 1063.05   937.3 1075.74
#Mann= 3 , 0 , 0
       0     0.1       0   454.5   0.045       0   469.5     0.1       0
Bank Sta=   454.5,   469.5
Exp/Cntr=0.3,0.1

Type RM Length L Ch R = 1 ,6048.9,399.928,399.996,399.589
XS GIS Cut Line= 3
     1779827.047      372635.199     1779422.384      372383.432
     1779043.854      372137.898
#Sta/Elev= 30
       0  987.70    38.9  989.27    87.5  988.54   116.7  981.91   136.2  974.16
   145.9  972.12   155.6  968.41   184.8  964.81   214.0  962.19   379.3  953.47
   437.7  953.32   457.1  951.38   467.7  948.85   476.6  946.64   482.7  946.91
   486.4  947.08   496.2  952.16   506.0  964.30   515.8  980.78   525.6  990.03
   535.4  996.11   545.3 1001.00   584.5 1014.91   613.9 1027.93   682.6 1044.25
   712.0 1047.64   780.7 1059.45   829.7 1071.46   868.9 1078.46   927.8 1091.72
#Mann= 3 , 0 , 0
       0     0.1       0   467.7   0.045       0   482.7     0.1       0
Bank Sta=   467.7,   482.7
Exp/Cntr=0.3,0.1

Type RM Length L Ch R = 1 ,5648.9,397.922,399.912,400.804
XS GIS Cut Line= 3
     1780025.021      372302.416     1779638.122      372059.855
     1779251.522      371819.452
#Sta/Elev= 30
       0 1052.41    68.0 1040.94    87.4 1031.28   106.9 1024.71   145.7 1005.44
   194.3  985.47   213.7  980.12   252.6  973.87   301.2  955.79   310.9  953.66
   427.5  945.75   446.9  941.63   447.7  941.66   456.6  941.95   462.7  945.05
   466.3  946.88   485.7  964.43   495.4  968.81   505.1  975.86   514.8  980.95
   534.1  985.78   582.6 1003.58   601.9 1008.07   660.1 1030.75   679.4 1036.02
   737.5 1057.31   756.9 1061.34   805.4 1076.09   824.7 1080.25   911.9 1108.52
#Mann= 3 , 0 , 0
       0     0.1       0   447.7   0.045       0   462.7     0.1       0
Bank Sta=   447.7,   462.7
Exp/Cntr=0.3,0.1

Type RM Length L Ch R = 1 ,5249,409.476,400.534,389.902
XS GIS Cut Line= 3
     1780227.447      372005.239     1779858.549      371741.743
     1779466.165      371493.317
#Sta/Elev= 30
       0 1100.54   125.4 1059.29   135.0 1058.28   154.3 1051.90   173.6 1048.00
   192.9 1040.73   212.2 1035.63   231.5 1026.10   250.8 1019.56   270.1 1007.13
   299.0  992.86   327.9  988.68   376.2  965.06   405.1  953.09   424.4  941.03
   444.4  937.58   453.3  937.54   459.4  938.43   511.4  945.63   540.4  952.63
   569.4  965.17   617.8  980.15   637.2  988.85   646.8  990.47   704.9 1013.06
   724.2 1018.68   772.6 1038.12   811.3 1051.09   869.4 1054.65   917.8 1061.94
#Mann= 3 , 0 , 0
       0     0.1       0   444.4   0.045       0   459.4     0.1       0
Bank Sta=   444.4,   459.4
Exp/Cntr=0.3,0.1

Type RM Length L Ch R = 1 ,4848.5,405.917,400.281,397.504
XS GIS Cut Line= 3
     1780434.960      371475.887     1779994.087      371373.017
     1779528.259      371328.561
#Sta/Elev= 30
       0 1107.85   134.9 1074.85   240.8 1052.91   269.7 1039.40   289.0 1028.17
   298.6 1025.20   317.9 1014.38   346.8 1003.27   375.7  997.79   385.3  994.02
   394.9  988.55   423.8  962.66   433.5  950.25     444  939.71   452.7  936.61
     459  936.78   579.5  946.53   608.7  950.77   637.9  958.25   657.4  966.32
   667.2  968.49   686.7  978.05   725.7  990.75   745.2  999.94   754.9 1001.57
   793.9 1021.36   803.7 1027.99   842.7 1042.56   901.2 1057.96   920.7 1061.54
#Mann= 3 , 0 , 0
       0     0.1       0     444   0.045       0     459     0.1       0
Bank Sta=     444,     459
Exp/Cntr=0.3,0.1

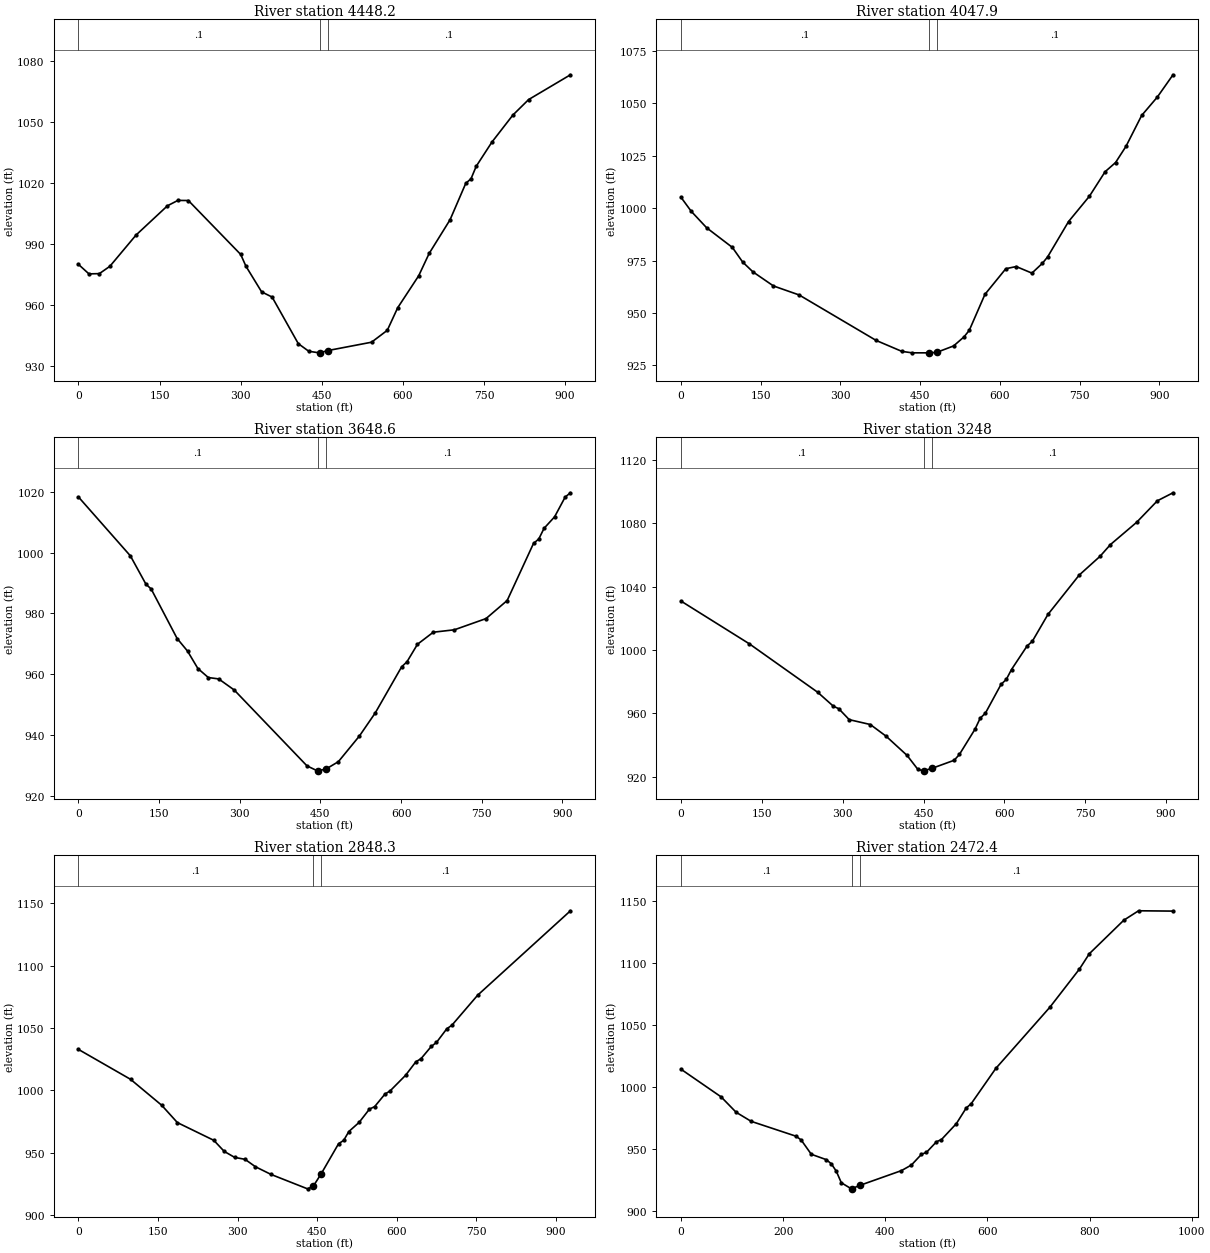
Type RM Length L Ch R = 1 ,4448.2,405.431,400.328,386.436
XS GIS Cut Line= 3
     1780468.141      370972.713     1780013.206      370980.423
     1779558.274      370988.297
#Sta/Elev= 30
       0  980.03    19.4  975.37    38.7  975.50    58.1  979.09   106.5  994.43
   164.6 1008.80   183.9 1011.44   203.3 1011.39   300.1  984.91   309.8  979.12
   338.8  966.54   358.2  963.99   406.6  941.12   426.0  937.38   445.3  936.61
   446.5  936.66   461.5  937.74   542.1  941.83   571.2  947.66   590.5  958.76
   629.3  974.44   648.6  985.38   687.3 1001.93   716.4 1019.84   726.1 1022.08
   735.7 1028.19   764.8 1040.09   803.5 1053.34   832.6 1060.94   910.0 1073.12
#Mann= 3 , 0 , 0
       0     0.1       0   446.5   0.045       0   461.5     0.1       0
Bank Sta=   446.5,   461.5
Exp/Cntr=0.3,0.1

Type RM Length L Ch R = 1 ,4047.9,385.547,399.28,418.618
XS GIS Cut Line= 3
     1780349.812      370492.409     1779891.575      370611.780
     1779524.364      370875.825
#Sta/Elev= 30
       0 1005.17    19.3  998.48    48.3  990.63    96.6  981.29   116.0  974.31
   135.3  969.63   173.9  962.91   222.3  958.61   367.2  936.92   415.5  931.71
   434.9  931.01   465.8  931.01   480.8  931.20   512.9  934.30   532.5  938.62
   542.4  941.74   571.9  958.90   611.2  971.14   630.8  972.16   660.3  969.03
   680.0  973.71   689.8  976.75   729.2  993.61   768.5 1005.71   798.0 1017.39
   817.7 1021.77   837.3 1029.49   866.8 1044.22   896.3 1053.00   925.8 1063.62
#Mann= 3 , 0 , 0
       0     0.1       0   465.8   0.045       0   480.8     0.1       0
Bank Sta=   465.8,   480.8
Exp/Cntr=0.3,0.1

Type RM Length L Ch R = 1 ,3648.6,413.744,400.608,392.996
XS GIS Cut Line= 3
     1780355.437      370381.476     1779923.969      370240.424
     1779469.654      370162.063
#Sta/Elev= 30
       0 1018.35    96.6  998.95   125.6  989.60   135.2  988.06   183.5  971.74
   202.8  967.61   222.1  961.86   241.5  958.89   260.8  958.43   289.7  954.78
   425.0  929.80   444.3  928.16   445.1  928.18   460.1  928.72   483.4  931.18
   522.6  939.65   552.0  947.24   601.1  962.43   610.9  964.05   630.5  969.84
   659.9  973.81   699.2  974.61   758.0  978.30   797.3  984.25   846.3 1003.05
   856.1 1004.52   865.9 1008.02   885.5 1011.81   905.2 1018.33   915.0 1019.73
#Mann= 3 , 0 , 0
       0     0.1       0   445.1   0.045       0   460.1     0.1       0
Bank Sta=   445.1,   460.1
Exp/Cntr=0.3,0.1

Type RM Length L Ch R = 1 ,3248,391.354,399.679,403.113
XS GIS Cut Line= 3
     1780320.951      369749.098     1779876.871      369863.054
     1779426.894      369926.209
#Sta/Elev= 30
       0 1030.90   126.8 1003.90   253.6  973.31   282.9  964.43   292.6  962.96
   312.1  956.02   351.2  952.95   380.4  945.60   419.4  933.45   439.0  924.81
   448.7  923.69   450.1  923.74   465.1  925.20   506.8  930.36   516.5  934.01
   545.5  950.00   555.1  956.93   564.8  960.13   593.8  978.30   603.5  981.39
   613.2  987.68   642.2 1002.59   651.8 1005.48   680.8 1022.46   738.8 1047.32
   777.5 1059.18   796.8 1066.59   845.2 1080.59   883.9 1094.25   912.9 1099.30
#Mann= 3 , 0 , 0
       0     0.1       0   450.1   0.045       0   465.1     0.1       0
Bank Sta=   450.1,   465.1
Exp/Cntr=0.3,0.1

Type RM Length L Ch R = 1 ,2848.3,374.32,375.911,379.967
XS GIS Cut Line= 3
     1780289.825      369521.210     1779840.500      369476.955
     1779364.471      369481.890
#Sta/Elev= 30
       0 1032.90    98.2 1008.92   157.0  988.08   186.5  974.20   255.2  959.97
   274.8  951.10   294.5  946.28   314.1  944.72   333.7  938.77   363.2  932.59
   431.9  921.05   442.7  923.15   457.7  933.16   490.4  957.24   500.1  959.93
   509.8  967.03   529.2  974.37   548.7  985.04   558.4  986.99   577.8  997.03
   587.5  999.58   616.7 1012.11   636.1 1022.97   645.8 1025.44   665.2 1035.29
   675.0 1038.50   694.4 1049.43   704.1 1052.32   752.7 1076.42   927.6 1144.12
#Mann= 3 , 0 , 0
       0     0.1       0   442.7   0.045       0   457.7     0.1       0
Bank Sta=   442.7,   457.7
Exp/Cntr=0.3,0.1

Type RM Length L Ch R = 1 ,2472.4,325.949,336.601,347.254
XS GIS Cut Line= 3
     1780269.721      369171.041     1779753.953      369105.257
     1779310.845      369124.806
#Sta/Elev= 30
       0 1014.33    78.5  992.06   107.9  979.66   137.3  972.36   225.6  960.31
   235.4  957.26   255.1  945.83   284.5  941.48   294.3  938.15   304.1  932.16
   313.9  922.88   333.6  917.97     335  918.18     350  920.74   431.7  932.66
   451.3  937.19   470.9  945.79   480.7  947.38   500.3  955.91   510.1  957.71
   539.2  970.50   558.5  983.11   568.2  986.53   616.4 1014.95   722.4 1064.31
   780.3 1095.07   799.6 1107.38   867.1 1134.39   896.0 1141.99   963.5 1141.73
#Mann= 3 , 0 , 0
       0     0.1       0     335   0.045       0     350     0.1       0
Bank Sta=     335,     350
Exp/Cntr=0.3,0.1

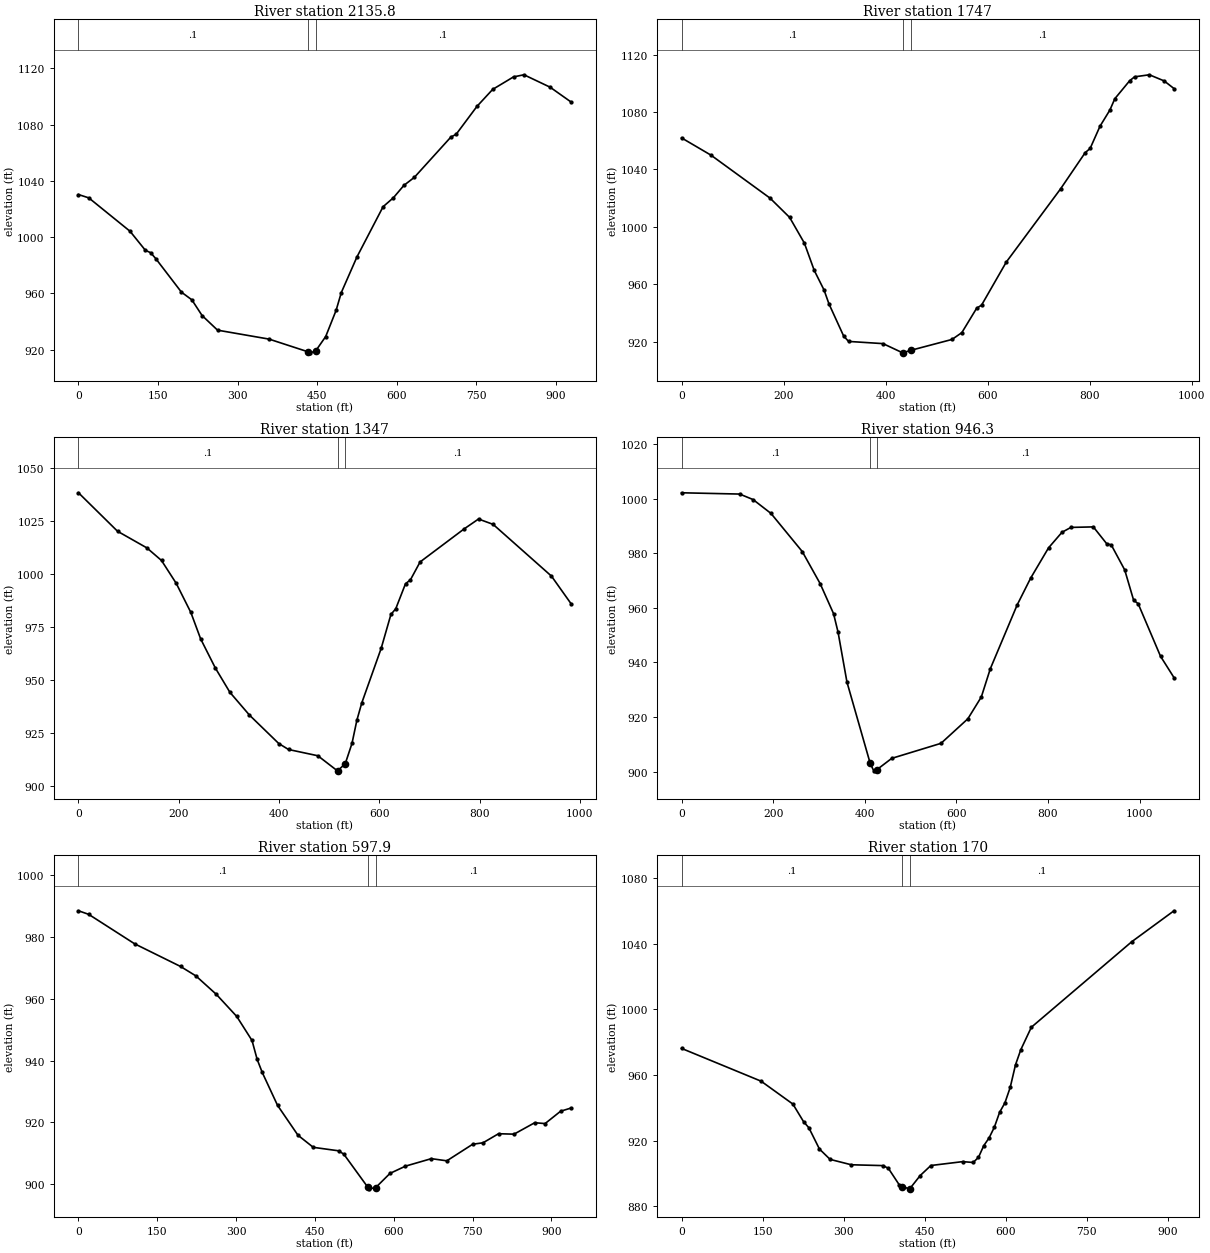
Type RM Length L Ch R = 1 ,2135.8,396.901,388.796,379.389
XS GIS Cut Line= 3
     1780329.072      369049.457     1779936.730      368780.575
     1779602.502      368475.731
#Sta/Elev= 30
       0 1030.32    19.4 1027.97    97.1 1004.24   126.2  990.63   135.9  989.01
   145.6  984.80   194.1  960.90   213.6  955.50   233.0  944.29   262.1  933.91
   359.2  927.55   431.9  918.61   436.8  917.79   446.9  919.12   465.9  929.39
   485.5  948.01   495.3  960.66   524.8  986.00   574.0 1021.66   593.6 1028.10
   613.3 1036.86   633.0 1042.57   701.8 1071.20   711.7 1073.16   751.0 1093.04
   780.5 1105.07   819.8 1113.97   839.5 1115.47   888.7 1106.66   928.0 1096.18
#Mann= 3 , 0 , 0
       0     0.1       0   431.9   0.045       0   446.9     0.1       0
Bank Sta=   431.9,   446.9
Exp/Cntr=0.3,0.1

Type RM Length L Ch R = 1 ,1747,399.703,400.027,400.638
XS GIS Cut Line= 3
     1780600.548      368591.083     1780171.486      368480.358
     1779658.686      368381.055
#Sta/Elev= 30
       0 1061.99    57.8 1049.94   173.4 1020.05   211.9 1006.59   240.8  988.69
   260.1  969.70   279.4  955.99   289.0  946.36   317.9  923.88   327.5  920.21
   395.0  918.68   433.5  912.26   434.4  912.34   449.4  914.01   530.2  921.59
   549.5  926.35   578.5  943.32   588.2  945.52   636.6  975.48   743.0 1026.46
   791.3 1051.70   801.0 1054.64   820.4 1070.16   839.7 1081.37   849.4 1089.27
   878.4 1101.76   888.1 1104.52   917.1 1105.95   946.1 1101.68   965.4 1096.35
#Mann= 3 , 0 , 0
       0     0.1       0   434.4   0.045       0   449.4     0.1       0
Bank Sta=   434.4,   449.4
Exp/Cntr=0.3,0.1

Type RM Length L Ch R = 1 ,1347,420.034,400.661,390.96
XS GIS Cut Line= 3
     1780640.568      368262.942     1780131.653      368129.495
     1779686.181      368032.192
#Sta/Elev= 30
       0 1038.33    77.9 1020.19   136.4 1012.35   165.6 1006.41   194.9  995.65
   224.1  981.92   243.6  969.48   272.8  955.79   302.0  944.26   341.0  933.52
   399.5  920.11   418.9  917.31   477.4  914.36   516.4  907.25   517.1  907.32
   532.1  910.65   545.5  920.21   555.2  931.09   564.9  939.21   603.7  965.01
   623.1  980.97   632.8  983.68   652.2  995.46   661.9  997.24   681.3 1005.72
   768.7 1021.23   797.8 1025.96   826.9 1023.44   943.3  999.04   982.1  986.12
#Mann= 3 , 0 , 0
       0     0.1       0   517.1   0.045       0   532.1     0.1       0
Bank Sta=   517.1,   532.1
Exp/Cntr=0.3,0.1

Type RM Length L Ch R = 1 ,946.3,345.587,348.402,340.067
XS GIS Cut Line= 3
     1780703.942      367592.524     1780349.901      367817.822
     1779706.676      367943.209
#Sta/Elev= 30
       0 1002.17   126.9 1001.70   156.1  999.69   195.2  994.61   263.5  980.64
   302.5  968.90   331.8  957.89   341.6  951.15   361.1  932.79   411.8  903.03
   419.6  900.28   426.8  900.76   458.8  904.85   566.4  910.36   625.0  919.35
   654.4  927.35   674.0  937.68   732.6  961.06   762.0  970.87   801.1  981.98
   830.5  987.70   850.0  989.48   898.9  989.67   928.3  983.46   938.0  983.08
   967.4  973.91   986.9  962.78   996.7  961.55  1045.6  942.26  1075.0  934.44
#Mann= 3 , 0 , 0
       0     0.1       0   411.8   0.045       0   426.8     0.1       0
Bank Sta=   411.8,   426.8
Exp/Cntr=0.3,0.1

Type RM Length L Ch R = 1 ,597.9,412.135,427.942,443.601
XS GIS Cut Line= 3
     1780556.022      367380.310     1780049.770      367649.206
     1779767.355      367878.891
#Sta/Elev= 30
       0  988.44    19.4  987.29   106.9  977.76   194.3  970.43   223.5  967.38
   262.3  961.43   301.2  954.28   330.3  946.50   340.1  940.38   349.8  936.15
   378.9  925.52   417.8  915.86   446.9  911.95   495.5  910.82   505.2  909.70
   550.8  899.03   553.8  898.53   565.8  898.95   592.9  903.52   622.4  905.87
   671.6  908.29   701.1  907.59   750.3  912.95   770.0  913.42   799.5  916.35
   829.0  916.21   868.4  919.91   888.1  919.63   917.6  923.62   937.3  924.65
#Mann= 3 , 0 , 0
       0     0.1       0   550.8   0.045       0   565.8     0.1       0
Bank Sta=   550.8,   565.8
Exp/Cntr=0.3,0.1

Type RM Length L Ch R = 1 ,170,111.157,114.667,119.696
XS GIS Cut Line= 3
     1780465.513      367377.359     1779972.020      367293.136
     1779561.331      367289.204
#Sta/Elev= 30
       0  976.26   147.2  956.27   206.1  942.29   225.8  931.57   235.6  927.86
   255.2  914.88   274.9  908.57   314.1  905.29   373.0  904.78   382.8  903.09
   402.5  893.23   407.5  891.99   422.1  890.61   422.5  890.74   441.7  898.74
   461.4  904.84   520.2  907.20   539.7  906.69   549.5  909.83   559.3  916.95
   569.1  921.65   578.9  928.22   588.6  937.27   598.4  943.05   608.2  952.46
   618.0  966.25   627.8  975.46   647.3  989.15   833.1 1041.31   911.3 1060.19
#Mann= 3 , 0 , 0
       0     0.1       0   407.5   0.045       0   422.5     0.1       0
Bank Sta=   407.5,   422.5
Exp/Cntr=0.3,0.1