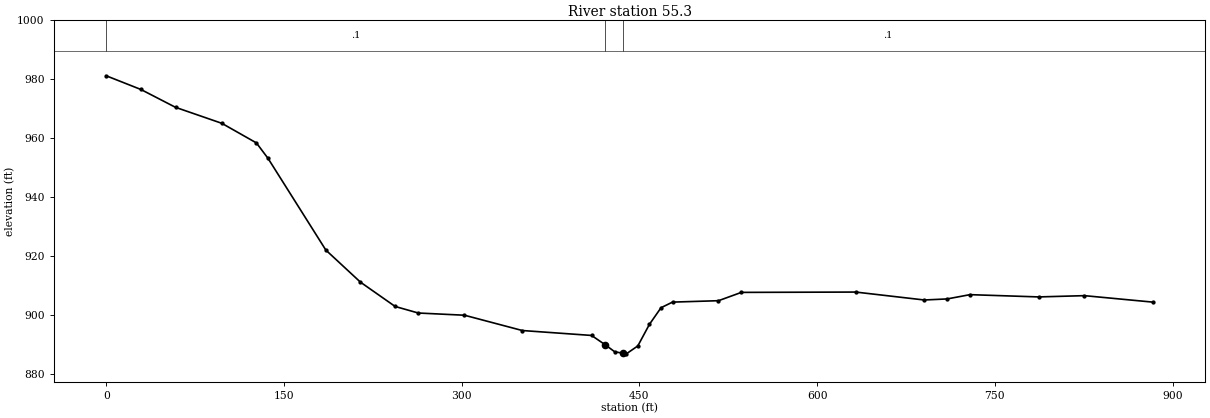
HEC-RAS study FnchsRn.prj: FnchsRn

--- FnchsRn.g01 (geometry) --- (continued)

Type RM Length L Ch R = 1 ,55.3,53.831,55.289,56.746
XS GIS Cut Line= 3
     1780511.327      367322.465     1780033.871      367182.594
     1779679.872      367028.624
#Sta/Elev= 30
       0  981.21    29.3  976.56    58.5  970.51    97.6  965.08   126.8  958.43
   136.6  953.18   185.4  922.07   214.6  911.19   243.9  902.94   263.4  900.72
   302.4  899.97   351.2  894.78   409.7  893.11   421.3  889.91   429.2  887.57
   436.3  887.06   439.0  886.87   448.7  889.55   458.5  896.87   468.3  902.52
   478.0  904.42   516.8  904.90   536.1  907.72   632.6  907.83   690.5  905.14
   709.8  905.50   729.1  906.95   787.0  906.18   825.7  906.61   883.6  904.41
#Mann= 3 , 0 , 0
       0     0.1       0   421.3   0.045       0   436.3     0.1       0
Bank Sta=   421.3,   436.3
Exp/Cntr=0.3,0.1